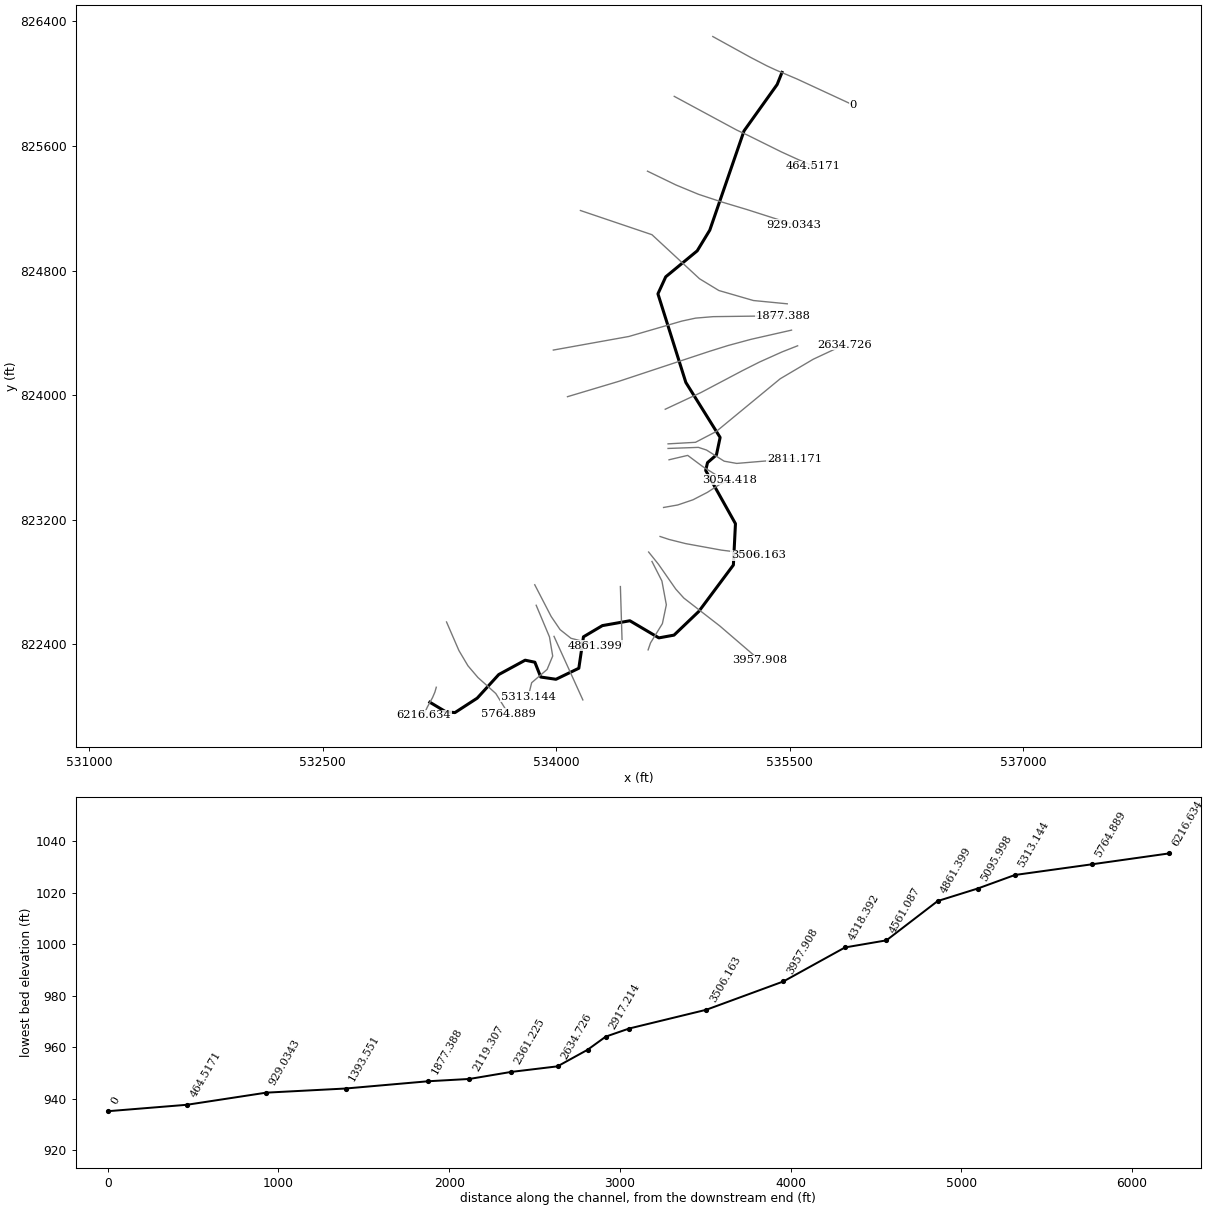
--- 8050_ras.prj (project) ---

Proj Title=8050
Current Plan=p01
Default Exp/Contr=0.3,0.1
English Units
Geom File=g01
Flow File=f01
Plan File=p01
Y Axis Title=Elevation
X Axis Title(PF)=Main Channel Distance
X Axis Title(XS)=Station
BEGIN DESCRIPTION:
RFD model 8050 exported to HEC-RAS
END DESCRIPTION:

--- 8050_ras.p01 (plan) ---

Plan Title=Plan 01
Program Version=4.10
Short Identifier=Plan 01
Geom File=g01
Flow File=f01
Subcritical Flow
Calc Critical at every XS
Secant Critical Depth

--- 8050_ras.f01 (steady flow) ---

Flow Title=Flow 01
Program Version=5.01
Number of Profiles= 6
Profile Names=10yr,25yr,50yr,100yr,100plus,500yr
River Rch & RM=8050,20,6216.634
 1870.01 2868.92 3776.02 4545.63 6636.62 7814.85
River Rch & RM=8050,20,5764.889
 1920.27 2947.18 3880.08 4671.89 6820.95  8004.4
River Rch & RM=8050,20,5313.144
 1930.83 2963.66 3902.05 4698.58 6859.93 8044.55
River Rch & RM=8050,20,5095.998
 1932.59 2966.41 3905.71 4703.03 6866.42 8051.24
River Rch & RM=8050,20,4861.399
 1935.82 2971.44 3912.41 4711.17 6878.31 8063.49
River Rch & RM=8050,20,4561.087
 1941.67 2980.59  3924.6 4725.98 6899.94 8085.74
River Rch & RM=8050,20,4318.392
 2301.15 3537.49 4662.97 5619.24 8204.09 9395.29
River Rch & RM=8050,20,3957.908
 2305.36 3544.09 4671.76 5629.94 8219.71 9411.01
River Rch & RM=8050,20,3506.163
 2364.05 3635.83 4794.13 5778.75 8436.97 9628.98
River Rch & RM=8050,20,3054.418
 2366.87 3640.23 4799.99 5785.87 8447.37 9639.36
River Rch & RM=8050,20,2917.214
 2420.07 3723.24 4910.55 5920.16 8643.44 9834.73
River Rch & RM=8050,20,2811.171
 2420.63 3724.11 4911.72 5921.58 8645.51 9836.79
River Rch & RM=8050,20,2634.726
 2422.59 3727.18  4915.8 5926.54 8652.75 9843.99
Boundary for River Rch & Prof#=8050,20,1
Up Type= 0
Dn Type= 2
Boundary for River Rch & Prof#=8050,20,2
Up Type= 0
Dn Type= 2
Boundary for River Rch & Prof#=8050,20,2
Up Type= 0
Dn Type= 2
Boundary for River Rch & Prof#=8050,20,2
Up Type= 0
Dn Type= 2
Boundary for River Rch & Prof#=8050,20,2
Up Type= 0
Dn Type= 2
Boundary for River Rch & Prof#=8050,20,2
Up Type= 0
Dn Type= 2

--- 8050_ras.g01 (geometry) ---

Geom Title=8050
Program Version=4.10

River Reach=8050,20
Reach XY= 30
533188.613187402822027.596727923533291.030749559821966.271972924
533349.975064993821961.103801876533492.743962348822053.697348237
533631.136060894 822205.36932373533800.804390222822297.584569931
533863.109750837 822284.55804877533900.827584893822189.427114367
 533998.69742766822175.032701448534145.499830872822245.871986389
 534175.24182874  822447.6734602534296.892437607822519.734178111
 534473.31693694822550.840892375534659.431546092822440.865873605
534756.884928972822458.589381382534916.114391774 822610.83582814
535138.146329314 822908.87324366535151.424758196823174.262093231
534960.090199381823516.299130097534972.078292251823566.468425572
535029.137173057823615.834117562  535052.9350214823728.098552868
534832.753111303824081.377322897534653.506913424824650.485614002
534703.653989047824759.752058774534905.757106155824926.560679883
534986.538277596825059.498367548535206.476444781 825696.97280702
535419.213786244825994.808584899535450.324523449826072.634496376

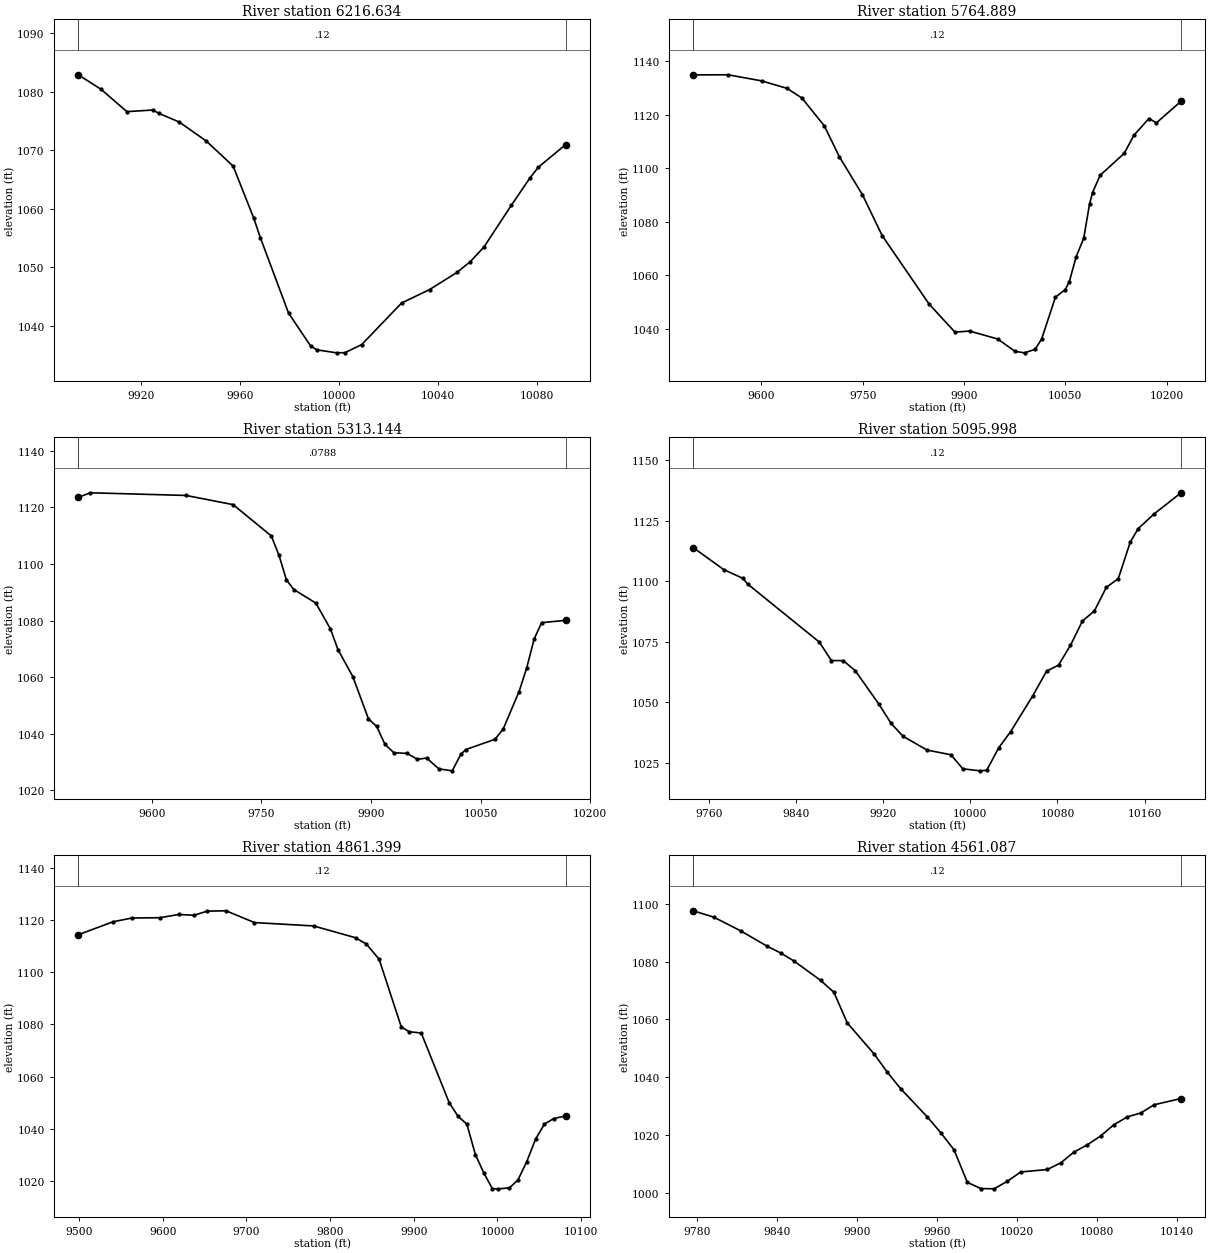
Type RM Length L Ch R = 1 ,6216.634,451.745100,451.745100,451.745100
XS GIS Cut Line= 6
533230.051253167822123.889658991533221.077919865822092.538074385
533205.982830285822057.355969714533172.745430483821996.924325012
533154.054015673821956.136649763533149.940749881821944.469081192
#Sta/Elev= 26
9894.6221082.8659903.8681080.376 9914.271076.5639924.672 1076.849927.2321076.268
9935.4351074.7869946.3171071.5539957.1981067.2499965.5161058.3749968.1981055.023
9979.5811042.1349988.5031036.5179990.9641035.855    99991035.337 10002.41035.367
10009.171036.76110025.261043.853 10036.61046.159 10047.61049.07510053.081050.943
 10058.61053.467 10069.61060.55810077.081065.21810080.561067.08310091.161070.801
10091.721070.814
#Mann= 3 , 0 , 0
9894.622    0.12       09894.622    0.12       010091.72    0.12       0
#XS Ineff= 2 , 0
       0                               0
Bank Sta=9894.622,10091.72
Exp/Cntr=0.3,0.1

Type RM Length L Ch R = 1 ,5764.889,451.745200,451.745200,451.745200
XS GIS Cut Line= 6
533295.829604955822543.090639799533375.393168178822359.564711283
533433.268974509822261.831895582533497.590894659822186.288056014
533612.336881614822083.508606931533693.767446409821952.328680722
#Sta/Elev= 30
 9499.081134.824 9551.031134.8669600.3891132.5879638.1471129.7869660.1581126.173
9693.1751115.838  9715.71104.1979749.7761090.0679778.9071074.8559848.3621049.323
9886.6371038.8339908.3211039.2279949.9651036.2719975.5991031.664 9989.811031.103
10005.27 1032.4210014.911036.20410035.481051.911 10049.81054.628   100561057.661
10066.251067.05110077.341073.86110086.021086.76110090.361090.91410101.631097.349
10137.411105.567 10151.41112.21810173.891118.54810185.031116.93810221.391124.988
#Mann= 3 , 0 , 0
 9499.08    0.12       0 9499.08    0.12       010221.39    0.12       0
#XS Ineff= 2 , 0
       09915.468                       0
Bank Sta=9499.08,10221.39
Exp/Cntr=0.3,0.1

Type RM Length L Ch R = 1 ,5313.144,217.145500,217.145500,217.145500
XS GIS Cut Line= 6
533871.654906005822650.300519958533956.968337089 822447.22577475
533977.685513109 822324.21555829533941.795232177 822238.21572639
533842.713378966822153.042422637533819.764081687822061.685582876
#Sta/Elev= 30
9499.1931123.491 9515.921125.0849646.8351124.139 9711.181120.8969763.4741109.844
9773.8841103.0779784.0921094.3569794.1991090.9439824.4031086.1439844.4331077.001
9854.5951069.7569875.0631060.1769896.3661045.2799907.6591042.6229918.9511036.297
9931.2721033.3189949.3631033.0989963.4061031.0029975.9351031.4469992.9281027.627
10011.051026.93710022.821032.76110029.561034.44810069.491038.05510080.741041.661
10102.471054.88910112.95 1063.21 10123.21073.49210133.391079.23810166.911080.067
#Mann= 3 , 0 , 0
9499.193  0.0788       09499.193  0.0788       010166.91  0.0788       0
#XS Ineff= 2 , 0
       0                               0
Bank Sta=9499.193,10166.91
Exp/Cntr=0.3,0.1

Type RM Length L Ch R = 1 ,5095.998,234.599600,234.599600,234.599600
XS GIS Cut Line= 2
533986.138734251822450.522457495534171.269402325822042.549318552
#Sta/Elev= 30
9745.5021113.9249773.5291104.8199791.1461101.1979795.4921098.863 9861.381074.857
9872.3621067.2539883.3431067.2059894.3251063.0589916.288 1049.099927.2691041.272
 9938.251035.9539960.213 1030.289982.1761028.3259993.158 1022.5210008.941021.686
10015.12 1021.94 10026.11031.21510037.081037.89510057.341052.66910070.031062.857
10081.011065.35110091.991073.54910102.971083.55710113.951087.72510124.931097.485
10135.921101.104 10146.91116.17110154.141121.71810168.861127.83410193.511136.539
#Mann= 3 , 0 , 0
9745.502    0.12       09745.502    0.12       010193.51    0.12       0
#XS Ineff= 2 , 0
       0                               0
Bank Sta=9745.502,10193.51
Exp/Cntr=0.3,0.1

Type RM Length L Ch R = 1 ,4861.399,300.311800,300.311800,300.311800
XS GIS Cut Line= 6
533862.350138553 822782.10467127533967.843812378822578.218634039
534025.209988876822493.840430345534095.003796013822438.317256764
534196.694985146822411.952271811 534248.22729015822390.706435493
#Sta/Elev= 30
9499.1661114.4999540.7741119.4919563.202 1120.939596.8441121.0549619.2721122.293
 9637.61 1121.989653.009 1123.579675.6891123.7179709.709 1119.189780.331 1117.89
9830.535 1113.359843.5031110.9039858.6251105.0899885.1271079.055 9894.611077.227
 9908.981076.7189942.4031049.9089952.9541044.6959963.4651041.6969973.6481030.013
9983.832 1022.859994.0151016.864   10001 1016.82 10014.31017.18310024.431020.194
10034.941027.22410045.531035.92210056.111041.70710067.121043.82410082.031044.913
#Mann= 3 , 0 , 0
9499.166    0.12       09499.166    0.12       010082.03    0.12       0
#XS Ineff= 2 , 0
       0                               0
Bank Sta=9499.166,10082.03
Exp/Cntr=0.3,0.1

Type RM Length L Ch R = 1 ,4561.087,242.695100,242.695100,242.695100
XS GIS Cut Line= 2
534412.396383643822770.501389995534423.824202627822404.811181411
#Sta/Elev= 30
9777.3211097.514 9792.83 1095.31 9812.841090.6099832.8491085.2759842.8541082.963
9852.8591080.2019872.8691073.4879882.8741069.3789892.8791058.8149912.888 1048.16
9922.8931041.8119932.8981036.1059952.9081026.3619962.9131020.9499972.918 1015.03
9982.9231003.7779992.9271001.63610002.931001.52610012.94 1004.1310022.94 1007.34
10042.951008.20810052.961010.49110062.961014.23310072.971016.73710082.971019.799
10092.98 1023.7110102.981026.37710112.991027.70910122.991030.54410143.191032.709
#Mann= 3 , 0 , 0
9777.321    0.12       09777.321    0.12       010143.19    0.12       0
#XS Ineff= 2 , 0
       0                               0
Bank Sta=9777.321,10143.19
Exp/Cntr=0.3,0.1

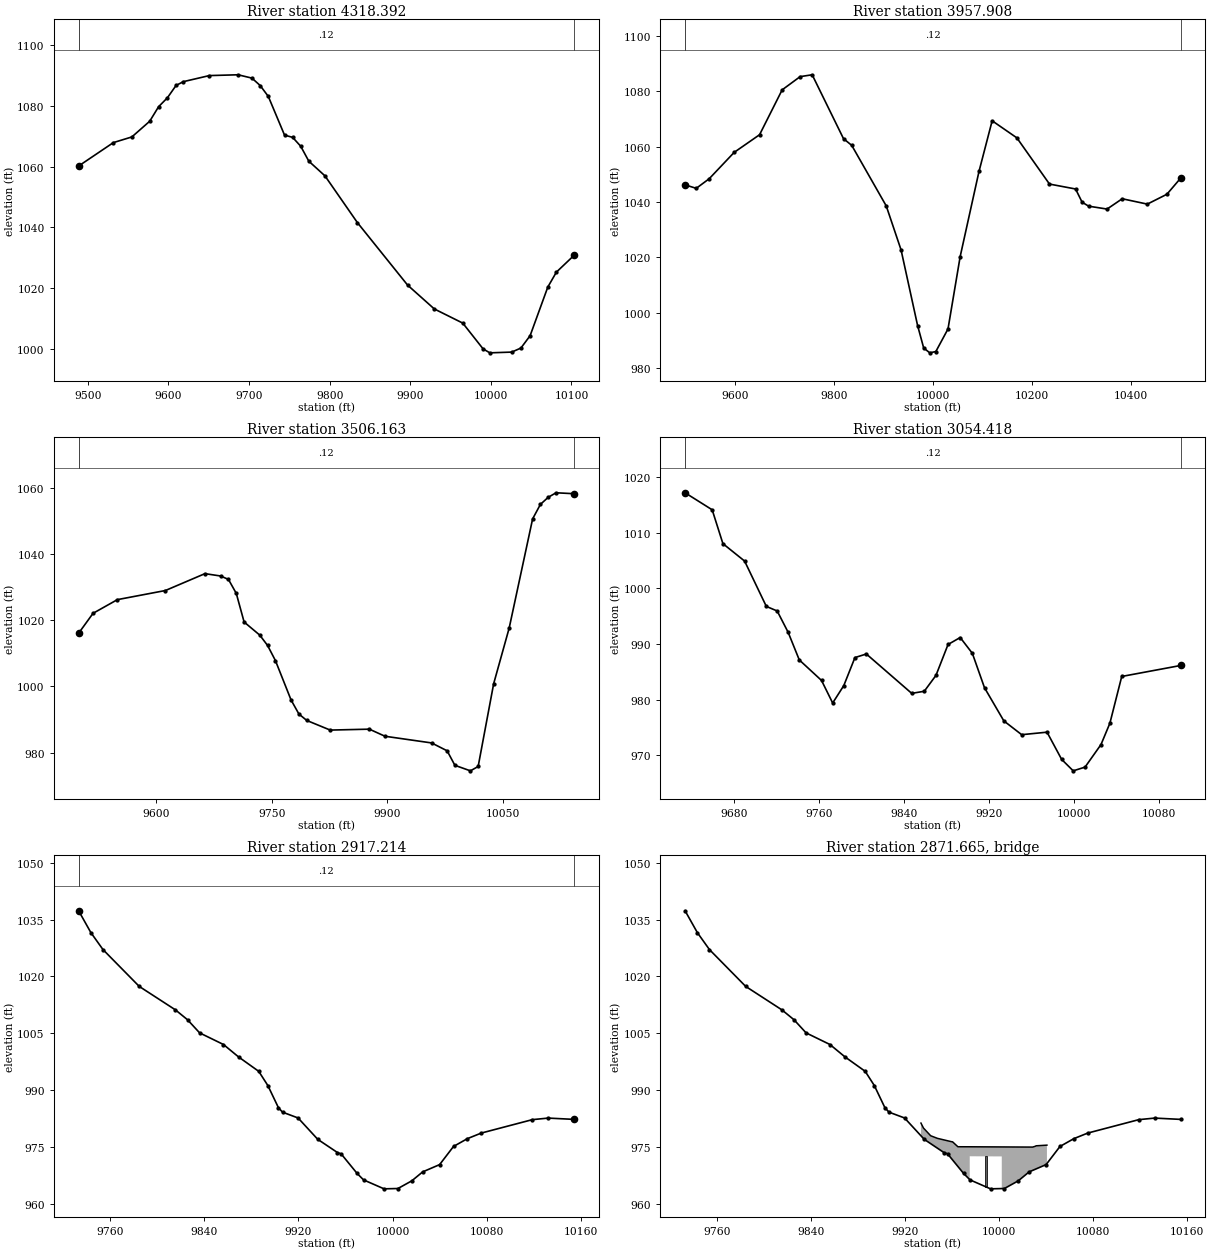
Type RM Length L Ch R = 1 ,4318.392,360.483500,360.483500,360.483500
XS GIS Cut Line= 6
534615.209415961822931.618806793 534679.07492712822806.236086664
534707.505131592822653.277058151534682.158345843822532.369463377
 534606.08775825822408.986056834534590.472463657822363.850607495
#Sta/Elev= 30
9488.4961060.1729531.5821067.8659554.5441069.7319576.6781074.8839587.7461079.675
9598.6661082.6059609.4151086.6619618.4791087.9059650.7071089.8979686.3551090.162
9703.5441089.0659713.7381086.6349723.8651083.043 9743.991070.3299754.0531069.592
9764.1151066.6499774.1271061.7589794.1441056.9399834.3521041.5869896.6861021.029
9929.8311013.192 9965.151008.5389990.3691000.0659998.724 998.764 10025.9999.0075
10037.311000.34310048.72  1004.410070.671020.38110081.32 1025.2910103.391030.844
#Mann= 3 , 0 , 0
9488.496    0.12       09488.496    0.12       010103.39    0.12       0
#XS Ineff= 2 , 0
       0                               0
Bank Sta=9488.496,10103.39
Exp/Cntr=0.3,0.1

Type RM Length L Ch R = 1 ,3957.908,451.745100,451.745100,451.745100
XS GIS Cut Line= 6
534593.745395702822992.286130655534656.908571696822913.762010718
534767.944426613822754.314754567534819.851507084822696.644920215
535050.506769047822517.729071373535306.073153672822298.011503607
#Sta/Elev= 30
9499.0611046.217 9521.641044.9669547.7631048.4279598.322 1057.969649.6371064.328
9695.2881080.5329731.6311085.307 9755.99 1085.989819.3421062.9019835.9441060.489
9905.7351038.6159935.7041022.7329969.119995.42269981.459987.2917  9993.8985.5491
10006.04986.023910030.62994.1776 10055.21020.30310093.271051.06910119.881069.363
10169.871063.194 10235.81046.50610288.551044.72710301.741039.96510314.931038.523
 10352.21037.47810382.88  1041.210433.621039.26510473.181042.82310500.971048.644
#Mann= 3 , 0 , 0
9499.061    0.12       09499.061    0.12       010500.97    0.12       0
#XS Ineff= 2 , 0
       0                               0
Bank Sta=9499.061,10500.97
Exp/Cntr=0.3,0.1

Type RM Length L Ch R = 1 ,3506.163,451.745200,451.745200,451.745200
XS GIS Cut Line= 6
534667.209366405823092.163226268534725.019231607823073.020445515
534830.913055707 823046.47705941535061.443097175823004.481265143
535213.768123095822985.736435274535298.212084804822971.431087332
#Sta/Elev= 30
9499.0471016.0539517.7871022.0689549.3891026.1959611.7021028.9439663.0611034.035
9683.4541033.3279693.6181032.2919703.7831028.0739713.9471019.4449734.2771015.484
9744.4411012.3599754.6061007.8039774.935995.90859785.099991.68239795.264989.7407
9825.758986.82929876.581987.1099 9896.91984.96749957.437982.95229977.594 980.577
9987.672 976.19610007.82974.530910017.89975.842910038.031000.82710058.181017.622
10088.611050.55810098.751054.945 10108.91057.08110119.04 1058.4410142.581058.159
#Mann= 3 , 0 , 0
9499.047    0.12       09499.047    0.12       010142.58    0.12       0
#XS Ineff= 2 , 0
       0                               0
Bank Sta=9499.047,10142.58
Exp/Cntr=0.3,0.1

Type RM Length L Ch R = 1 ,3054.418,137.204000,137.204000,137.204000
XS GIS Cut Line= 6
534689.726733953 823278.40382418534780.789613008823294.534175634
534878.565303355 823327.72329621534970.915029138823375.404466033
535050.669230878823426.881348446535115.566218168823456.417535856
#Sta/Elev= 30
9633.8741017.1949659.3551014.1369669.4471008.0569689.8711004.9229710.296996.7812
9720.508995.95619730.829992.12419741.299987.1653 9762.24983.4726 9772.71979.4255
 9783.18 982.5569793.651 987.5889804.393988.23179847.066981.15849858.874981.5318
9869.893984.38729881.253989.93889892.684991.18999904.116988.35069915.548982.1651
9933.742976.21039950.531973.73219974.371974.18329988.124969.2963    9999967.2372
10010.13967.904610025.15971.9597 10033.5975.785710044.66984.193410100.07986.1648
#Mann= 3 , 0 , 0
9633.874    0.12       09633.874    0.12       010100.07    0.12       0
#XS Ineff= 2 , 0
       09894.445        10067.73       0
Bank Sta=9633.874,10100.07
Exp/Cntr=0.3,0.1

Type RM Length L Ch R = 1 ,2917.214,106.043400,106.043400,106.043400
XS GIS Cut Line= 5
534724.835374981823584.763462901534844.746260971823612.916453511
534940.232372075823541.735897973535061.760149837823465.347009078
535096.632865399823472.321552187
#Sta/Elev= 30
9733.0991037.302 9743.541031.5419753.8121027.0839784.6281017.3889815.4441011.202
9825.7161008.6039835.987 1005.159856.2711002.088 9869.06998.82459886.248 995.025
9894.005991.2809 9902.98 985.4579906.478984.27629919.712982.74529936.443977.1169
9953.175973.64269956.369 973.2769969.907968.13989975.368966.44329992.811964.0843
10004.62964.170410016.43966.195910025.61968.542610040.06970.464710051.87975.2427
10063.68977.302410075.49978.770510118.91982.304210132.41982.713810154.47 982.372
#Mann= 3 , 0 , 0
9733.099    0.12       09733.099    0.12       010154.47    0.12       0
#XS Ineff= 2 , 0
       0                10126.46       0
Bank Sta=9733.099,10154.47
Exp/Cntr=0.3,0.1

Type RM Length L Ch R = 3 ,2871.665,,,
BEGIN DESCRIPTION:
END DESCRIPTION:
Bridge Culvert--1,0,-1,-1, 0
Deck Dist Width WeirC Skew NumUp NumDn MinLoCord MaxHiCord MaxSubmerge Is_Ogee
46.296000,13.451400,2.6,0, 16, 16, , , 0.95, 0, 0,0,,
 9933.66 9935.80 9941.89 9947.65 9959.50 9960.41 9960.52 9965.05 9975.14 9975.14
10002.3710002.3710028.5810030.6510031.6610040.77
  981.40  980.09  978.07  977.38  976.51  976.47  976.47  975.17  975.16  975.16
  975.12  975.12  975.08  975.27  975.42  975.59
  -18.60  -19.91  -21.93  -22.62  -23.49  -23.53  -23.53  -24.83  -24.84  972.66
  972.62  -24.88  -24.92  -24.73  -24.58  -24.41
 9933.66 9935.80 9941.89 9947.65 9959.50 9960.41 9960.52 9965.05 9977.26 9977.26
10004.4910004.4910028.5810030.6510031.6610040.77
  981.40  980.09  978.07  977.38  976.51  976.47  976.47  975.17  975.15  975.15
  975.12  975.12  975.08  975.27  975.42  975.59
  -18.60  -19.91  -21.93  -22.62  -23.49  -23.53  -23.53  -24.83  -24.85  972.65
  972.62  -24.88  -24.92  -24.73  -24.58  -24.41
Pier Skew, UpSta & Num, DnSta & Num=  ,9988.75, 2 ,9990.87, 2 , 0 , 0 , 0 ,,
    2.00    2.00
  -24.86  975.14
    2.00    2.00
  -24.86  975.14
BR Coef=-1 , 0 , 0 ,, 0 ,,,0.8,0,1,0,
WSPro=,,,, 1 ,,,, 0 ,,,, 0 ,,,,-1 ,-1 ,-1 , 0 , 0 , 0 , 0 , 0
BC Design=,, 0 ,, 0 ,,,,,,

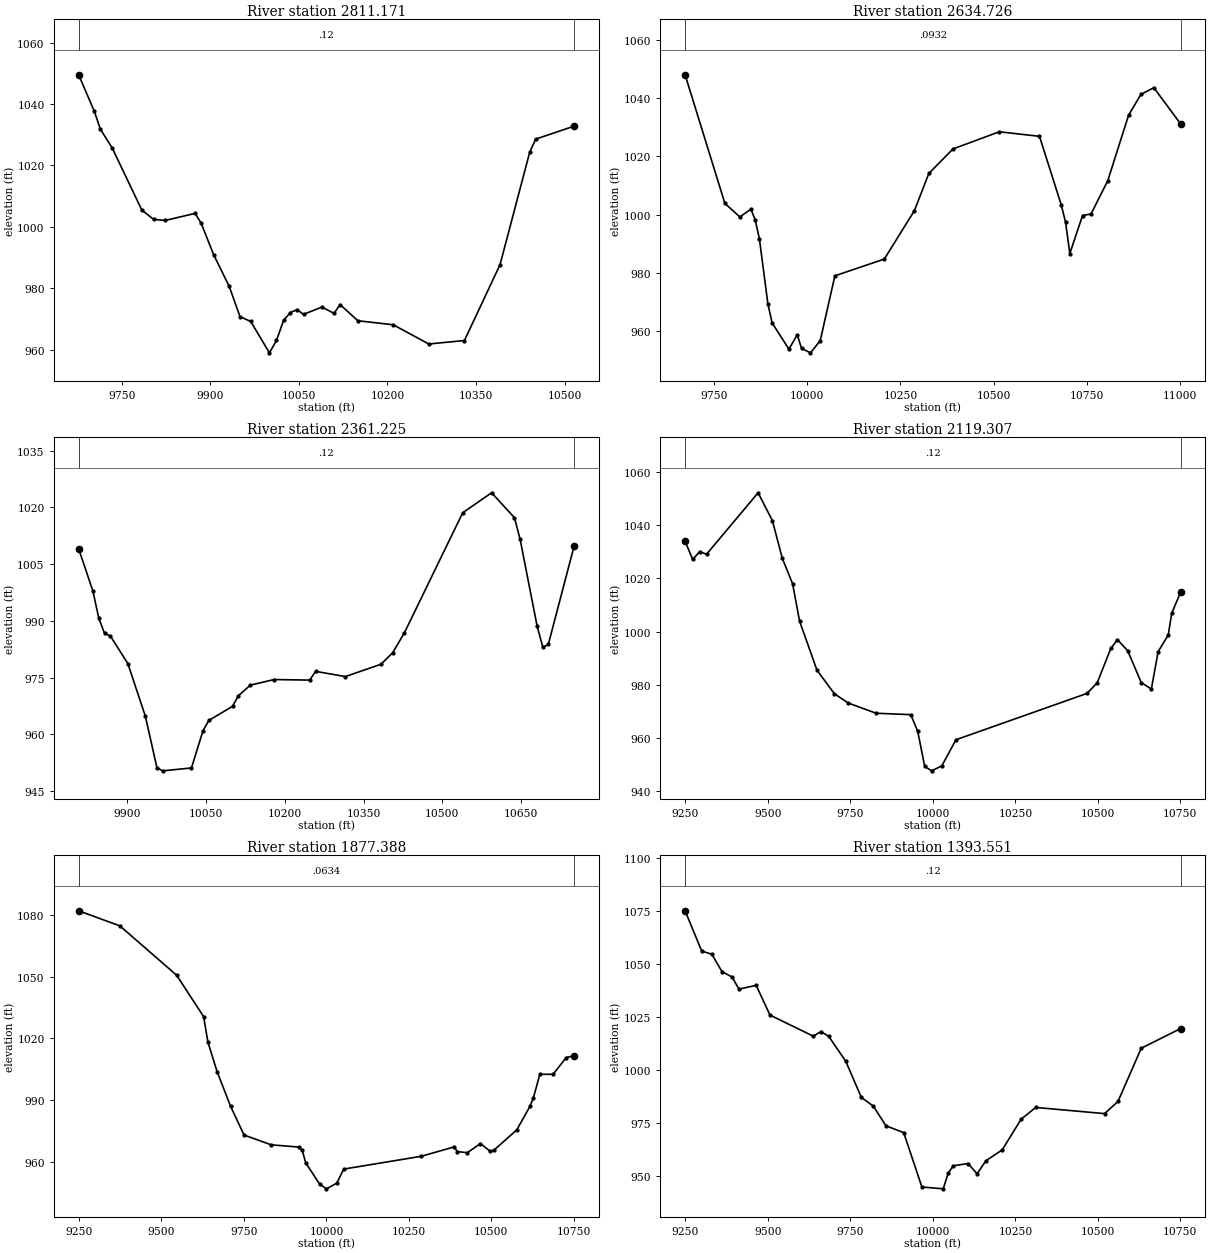
Type RM Length L Ch R = 1 ,2811.171,176.444600,176.444600,176.444600
XS GIS Cut Line= 6
 534718.55656448823657.476635709534913.496931255823664.341091603
534965.308693796823647.354329452 535079.02100262823575.665286064
535159.377830327823561.346733585535529.922197206823592.426079988
#Sta/Elev= 30
9677.1351049.5479703.7871037.6239713.8421031.8549733.9521025.7189784.1431005.492
9804.1661002.4359824.1741002.1159874.4451004.4059884.7151001.1649905.749990.9725
9932.167980.6133 9950.47970.75489968.615 969.19610000.25958.979310012.22963.0005
10024.26969.571510035.81972.114710047.11973.044410058.04971.519410089.33973.8905
10109.74 971.826 10119.8974.719610149.93969.437410209.97968.120610270.19961.8587
10330.51962.991610390.84987.716410441.11 1024.3410451.171028.59310516.381032.824
#Mann= 3 , 0 , 0
9677.135    0.12       09677.135    0.12       010516.38    0.12       0
#XS Ineff= 2 , 0
       0                10048.55       0
Bank Sta=9677.135,10516.38
Exp/Cntr=0.3,0.1

Type RM Length L Ch R = 1 ,2634.726,273.500700,273.500700,273.500700
XS GIS Cut Line= 6
 534718.55656448 823686.96934709534894.742976397823696.862156108
535027.635951579823766.069613442535438.817622393824105.071599841
535650.968341261824230.465687394535852.100961387824324.609182939
#Sta/Elev= 30
9672.7021048.0199779.3131003.8579819.376999.21169849.1661001.8579860.731998.1205
9872.005991.57579894.555969.3848 9905.83962.82719950.929 953.7969973.478  958.75
9984.753954.048410008.74952.528210034.92956.717910074.18978.985510206.72984.7355
10287.491001.398   103261014.133 10390.71022.54810514.961028.44710622.581026.882
10680.841003.38410692.38997.441710703.96986.641210738.03999.691310760.721000.202
10805.681011.66710861.45 1034.1510894.371041.26710929.081043.58811000.941031.149
#Mann= 3 , 0 , 0
9672.702  0.0932       09672.702  0.0932       011000.94  0.0932       0
#XS Ineff= 2 , 0
       0                               0
Bank Sta=9672.702,11000.94
Exp/Cntr=0.3,0.1

Type RM Length L Ch R = 1 ,2361.225,241.918500,241.918500,241.918500
XS GIS Cut Line= 6
534700.453141746823909.346100145 534929.53024195824016.383479932
535197.972792867824158.075640379535305.216621516824212.162314453
535451.061342364824277.606069744535550.742159069824316.825790098
#Sta/Elev= 30
9807.4541009.047 9834.66997.88189845.742990.73889856.825986.68359867.908985.9978
9901.157978.70529934.406964.81839956.547951.17739967.489950.339310022.31 951.105
10044.32960.980110055.33963.668110100.43967.388510111.74970.208910134.35972.9963
10179.58974.481310247.43974.334410258.73 976.64310315.27975.265410382.93978.5159
10405.33981.552510427.73 986.844 10538.81018.59610593.751023.86810637.251017.285
10648.081011.54910680.32  988.6610691.35982.982210701.81983.819410750.961009.833
#Mann= 3 , 0 , 0
9807.454    0.12       09807.454    0.12       010750.96    0.12       0
#XS Ineff= 2 , 0
       0                               0
Bank Sta=9807.454,10750.96
Exp/Cntr=0.3,0.1

Type RM Length L Ch R = 1 ,2119.307,241.918400,241.918400,241.918400
XS GIS Cut Line= 6
534072.654770938823989.855607574534403.234115606824088.760015542
534983.993370971 824281.03549118535103.351252536824318.342095856
535251.143798433824358.279834413535511.510811111824417.370580156
#Sta/Elev= 30
9249.0081033.8649272.277 1027.089293.1041030.0429313.9311029.0579470.3171052.163
9513.6791041.659 9543.59 1027.559574.9921017.9059595.9391003.9419648.613985.4956
9701.288976.63559743.427973.12929827.705969.28479933.054968.74849954.123962.4646
9975.193949.31379996.263947.627610027.26 949.52110069.98959.320110467.26976.7367
10498.19980.744210539.21993.633410559.53996.930310590.48992.7852 10631.5980.8286
10662.26978.371910682.77992.444710713.53998.726810723.79  1006.810750.971014.836
#Mann= 3 , 0 , 0
9249.008    0.12       09249.008    0.12       010750.97    0.12       0
#XS Ineff= 2 , 0
       0                               0
Bank Sta=9249.008,10750.97
Exp/Cntr=0.3,0.1

Type RM Length L Ch R = 1 ,1877.388,483.836900,483.836900,483.836900
XS GIS Cut Line= 6
533981.674180735824289.345808065 534466.98799731824376.622647003
 534807.14695915824475.478675998534895.728616021824494.519667977
 535008.95685714824503.955516295535458.906152344824509.723030972
#Sta/Elev= 30
9249.0191082.226 9374.061074.8649546.4471050.7549627.8251030.6419640.9511018.173
9668.6341003.8879709.501986.95729750.421972.93989832.834968.17349916.185967.0787
 9926.67965.60429937.155959.43559979.095949.123410000.07946.727810031.48 949.493
10052.42956.354510286.89962.573410386.91967.143610396.91964.912810426.91964.3048
10466.91968.810910496.91964.936410506.91965.446910576.91975.449210616.92986.9134
10626.92990.815610646.931002.55410686.971002.53510727.01 1010.7110750.941011.565
#Mann= 3 , 0 , 0
9249.019  0.0634       09249.019  0.0634       010750.94  0.0634       0
#XS Ineff= 2 , 0
       0                               0
Bank Sta=9249.019,10750.94
Exp/Cntr=0.3,0.1

Type RM Length L Ch R = 1 ,1393.551,464.517100,464.517100,464.517100
XS GIS Cut Line= 6
534155.767217725825185.624173245 534615.13019371825030.272123675
534920.527985674824747.384144774535044.881226691824671.740338831
535266.623115696824607.541487371535484.105529489 824586.34063509
#Sta/Elev= 30
9249.0831075.1999299.4211056.1849330.0941054.6889360.7681046.5039391.6391043.887
9412.3151038.2059464.4851039.9849506.3411025.954 9637.551015.9959660.9381018.167
9684.325 1015.919736.1261004.1099783.189987.08619819.747982.91769857.721973.6794
9911.585970.44229966.725944.777710031.37943.905210046.68951.3966   10062954.7934
10106.58955.848610134.03951.002310160.53957.146410210.11 962.29910267.66976.8052
10311.73982.340310520.38979.426410560.94985.154510631.531010.294 10750.9 1019.59
#Mann= 3 , 0 , 0
9249.083    0.12       09249.083    0.12       0 10750.9    0.12       0
#XS Ineff= 2 , 0
       0                               0
Bank Sta=9249.083,10750.9
Exp/Cntr=0.3,0.1

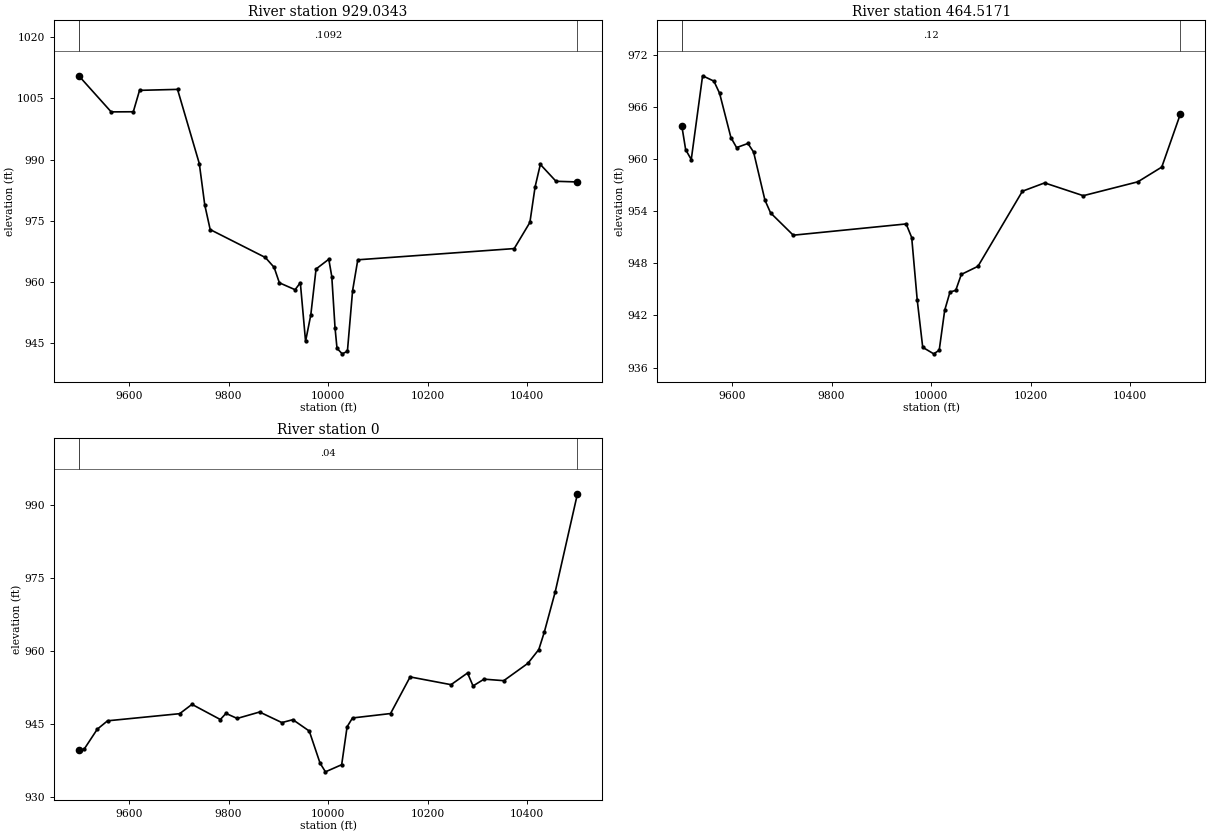
Type RM Length L Ch R = 1 ,929.0343,464.517200,464.517200,464.517200
XS GIS Cut Line= 6
534586.442794512825438.233756062534769.126725599825349.726868535
534914.223016353825289.640146929535061.196581569825241.028058033
535227.170134429 825191.16325564535526.025365428825095.541671172
#Sta/Elev= 30
9499.0391010.5549564.1061001.6919608.5531001.7219621.1331006.9779697.4481007.214
9741.205988.99789752.124978.86829763.043972.80229873.909965.94799891.519963.5283
 9902.05959.73629933.642958.04129944.173959.75429954.704945.36939965.235 951.874
9975.766963.126310001.38965.519810007.38961.271410013.91948.685410017.88943.6479
10028.33942.296910038.77942.922310049.21957.826810059.65965.381110373.93968.1364
10405.42974.555510415.92983.307610426.42988.794410457.92984.652710500.99 984.491
#Mann= 3 , 0 , 0
9499.039  0.1092       09499.039  0.1092       010500.99  0.1092       0
#XS Ineff= 2 , 0
       0                               0
Bank Sta=9499.039,10500.99
Exp/Cntr=0.3,0.1

Type RM Length L Ch R = 1 ,464.5171,464.517100,464.517100,464.517100
XS GIS Cut Line= 6
534758.335244415825918.696902866535159.136813055825702.469399054
535234.613315218825666.962524229535445.821771807825562.223702051
535559.752975157825510.289729708535653.767722398825470.259357537
#Sta/Elev= 30
 9499.01963.83179506.742961.09199517.984959.95539540.756969.60259563.528968.9844
9574.914967.58649597.686962.48499609.072961.33329631.844961.8079 9643.23960.8212
9666.002955.28499677.388953.81229722.932951.24379949.751952.54129960.917950.9751
9971.987943.79529983.057938.332510005.16937.581910016.19937.998510027.23942.6037
10037.84944.693310049.43944.896110060.59946.726510094.08 947.66310183.38956.3098
10228.03957.267410305.66955.793810415.37957.393310463.36 959.08810500.98965.2334
#Mann= 3 , 0 , 0
 9499.01    0.12       0 9499.01    0.12       010500.98    0.12       0
#XS Ineff= 2 , 0
       0                               0
Bank Sta=9499.01,10500.98
Exp/Cntr=0.3,0.1

Type RM Length L Ch R = 1 ,       0,0.000000,0.000000,0.000000
XS GIS Cut Line= 6
535005.866885986826302.938366433535246.348369105826170.217566676
535353.009439651 826114.79457739535407.898288394826089.274302967
535547.444583669826029.964573281535905.777865868825863.947677732
#Sta/Elev= 30
9499.016939.52969509.447939.6758 9536.14943.83279556.836945.55889701.706947.0234
9726.463948.9396 9783.44945.82369794.709947.08099817.248946.04569862.326947.3654
9907.114945.1925 9929.17  945.79 9962.12943.45349983.798936.85869994.638935.0696
10027.24936.536210038.12944.3272   10049946.144310125.45947.052410164.76954.5778
10246.98952.985310280.13955.386810291.18952.723110313.27954.1192 10352.9953.8081
10401.39957.372110423.33960.2081 10434.3963.758710456.25972.039310500.99992.2227
#Mann= 3 , 0 , 0
9499.016    0.04       09499.016    0.04       010500.99    0.04       0
#XS Ineff= 2 , 0
       0                               0
Bank Sta=9499.016,10500.99
Exp/Cntr=0.3,0.1